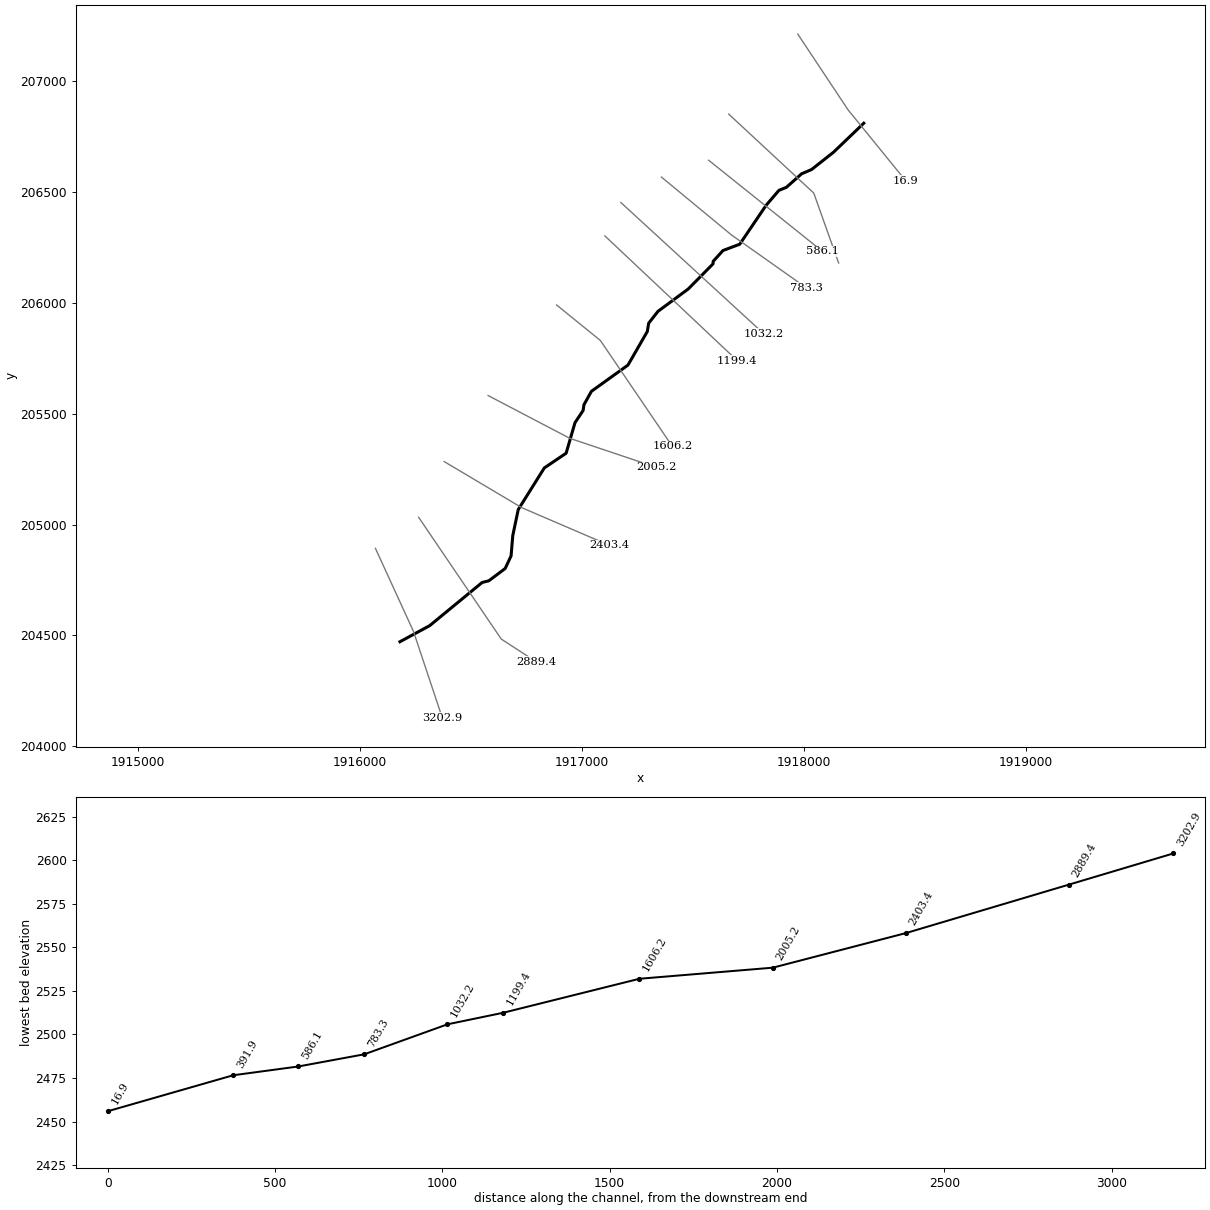
--- SngBrnch.prj (project) ---

Proj Title=SngBrnch
Current Plan=p01
Geom File=g01
Flow File=f01
Plan File=p01
DSS Export Rating Curves=0
DSS Export Rating Curve Sorted=0
DSS Export Volume Flow Curves=0
DXF OffsetX=0
DXF OffsetY=0
DXF ScaleX=0
DXF ScaleY=0

--- SngBrnch.p01 (plan) ---

Plan Title=Floodplain
Program Version=4.00
Geom File=g01
Flow File=f01
K Sum by GR=0
Std Step Tol=0.01
Critical Tol=0.01
Num of Std Step Trials=20
Max Error Tol=0.3
Flow Tol Ratio=0.001
Split Flow NTrial=30
Split Flow Tol=0.02
Split Flow Ratio=0.02
Log Output Level=0
Friction Slope Method=1
Unsteady Friction Slope Method=2
Unsteady Bridges Friction Slope Method=1
Global Log Level=0
CheckData=False
Run HTab=0
Run UNet=0
Run PostProcess=0
UNET Theta=0
UNET Theta Warmup=0
UNET ZTol=0
UNET ZSATol=0
UNET MxIter=0
UNET MaxInSteps=0
UNET DtIC=0
UNET DtMin=0
UNET MaxCRTS=0
UNET WFStab=0
UNET SFStab=0
UNET WFX=0
UNET SFX=0
UNET DSS MLevel=0
UNET DZMax Abort=0
UNET Convert EG Bridges=0
UNET Use Existing IB Tables=0
UNET Froude Limit=0
UNET Froude Power=0
Write IC File=0
Echo Input=False
Echo Output=False
Write Detailed=0

--- SngBrnch.f01 (steady flow) ---

Flow Title=NFF Regression Equation
Program Version=4.00
Number of Profiles=1
Profile Names=P100yr
River Rch & RM=SngBrnch,Main      ,3202.9
523.3031
River Rch & RM=SngBrnch,Main      ,16.9
560.1061
Boundary for River Rch & Prof#=SngBrnch,Main      ,1
Up Type=0
Dn Type=3
Dn Slope=0.038357

--- SngBrnch.g01 (geometry) ---

Geom Title=USGS 3m DEM
Program Version=4.00

River Reach=SngBrnch     ,Main
Reach XY= 30
     1916181.660      204471.937     1916315.116      204544.033
     1916552.014      204738.895     1916581.850      204746.354
     1916655.667      204801.780     1916682.211      204858.659
     1916689.795      204949.667     1916714.443      205067.218
     1916831.994      205254.920     1916930.087      205321.014
     1916970.202      205458.821     1917006.660      205513.508
     1917010.566      205539.550     1917044.070      205599.897
     1917208.701      205718.070     1917295.914      205869.429
     1917302.199      205907.140     1917343.910      205960.227
     1917480.287      206060.993     1917592.285      206174.474
     1917592.285      206185.127     1917636.714      206234.196
     1917712.286      206262.674     1917831.179      206438.016
     1917888.974      206505.437     1917922.574      206519.049
     1917991.041      206579.930     1918035.945      206599.175
     1918134.537      206676.910     1918271.048      206807.733

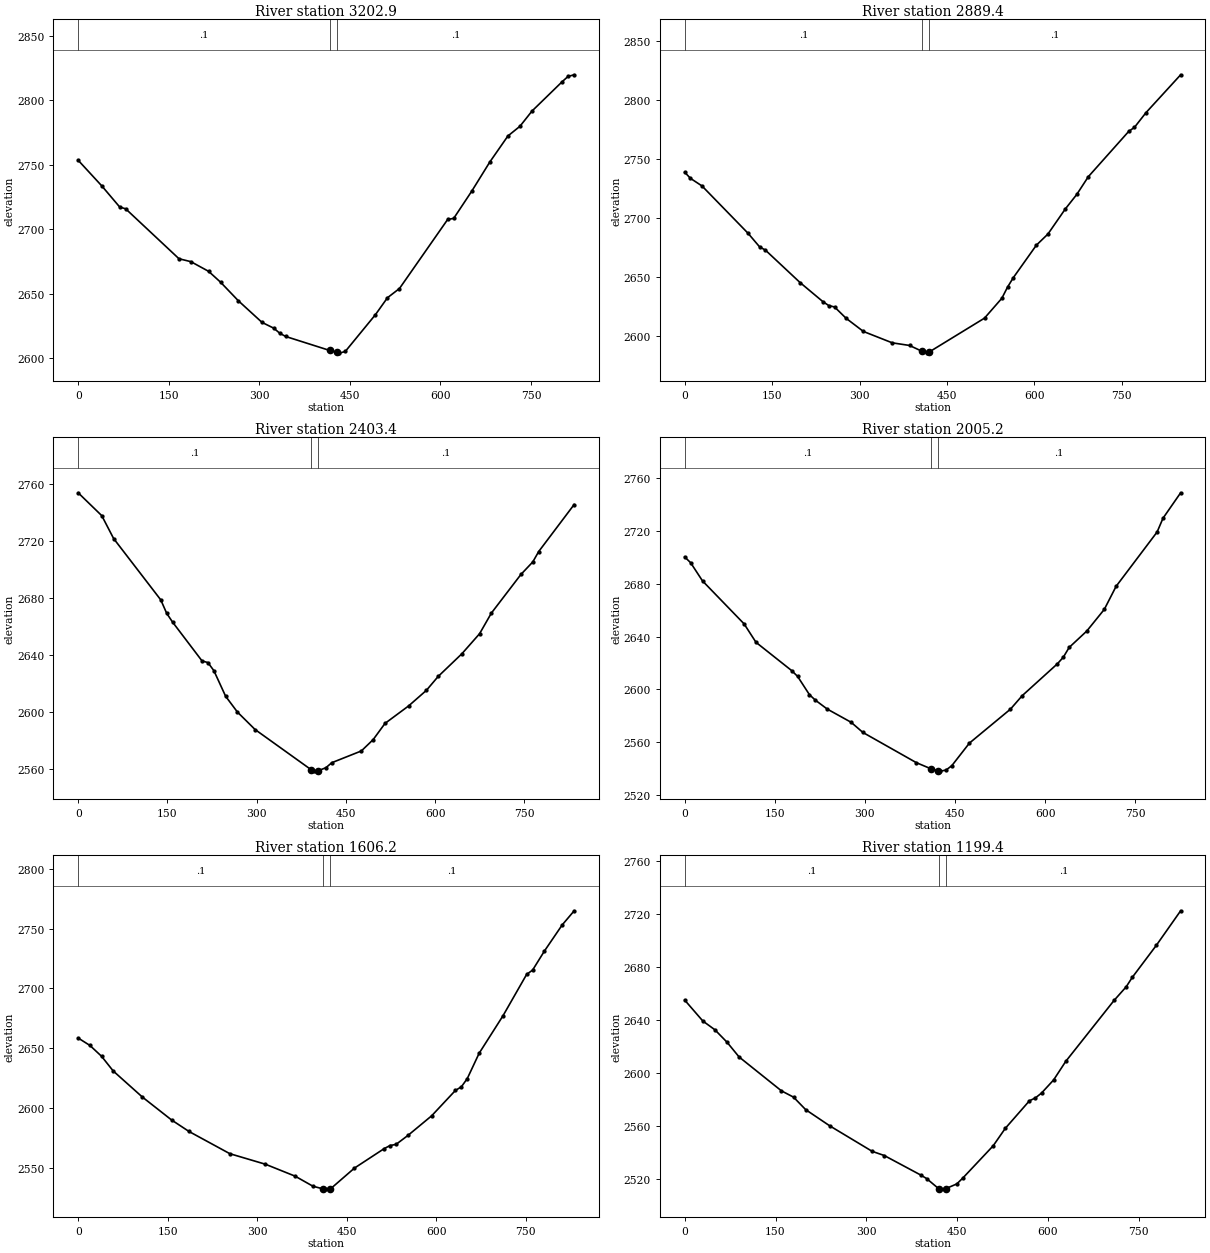
Type RM Length L Ch R = 1 ,3202.9,308.7,313.3,319.2
XS GIS Cut Line= 3
     1916070.959      204892.910     1916242.709      204517.972
     1916372.044      204129.973
#Sta/Elev= 30
       0 2753.35    39.3 2733.38    68.7 2717.14    78.6 2715.75   166.9 2677.04
   186.6 2674.78   216.0 2667.27   235.7 2658.89   265.1 2644.52   304.4 2627.70
   324.0 2623.18   333.8 2619.29   343.7 2616.77   416.6 2605.93   428.6 2604.53
   432.4 2603.87   442.3 2605.14   492.2 2633.63   512.2 2646.81   532.1 2653.97
   611.9 2707.49   621.9 2708.33   651.8 2729.44   681.7 2752.02   711.7 2772.22
   731.6 2779.72   751.6 2791.54   801.4 2814.21   811.4 2818.43   821.4 2819.62
#Mann= 3 , 0 , 0
       0     0.1       0   416.6   0.045       0   428.6     0.1       0
Bank Sta=   416.6,   428.6
Exp/Cntr=0.3,0.1

Type RM Length L Ch R = 1 ,2889.4,476.6,485.8,496.6
XS GIS Cut Line= 3
     1916265.896      205032.352     1916638.050      204483.807
     1916795.891      204381.424
#Sta/Elev= 30
       0 2739.10     9.9 2733.89    29.7 2727.46   108.8 2687.35   128.6 2675.85
   138.5 2673.14   197.9 2645.70   237.4 2629.41   247.3 2626.17   257.2 2624.99
   277.0 2615.40   306.7 2604.25   356.2 2594.62   385.8 2592.41   407.4 2587.43
   415.5 2585.91   419.4 2586.81   514.5 2615.54   544.2 2632.32   554.0 2641.78
   563.9 2649.79   603.5 2677.32   623.3 2686.72   653.0 2707.88   672.8 2720.26
   692.6 2735.27   761.9 2773.62   771.8 2777.08   791.6 2789.53   851.0 2821.54
#Mann= 3 , 0 , 0
       0     0.1       0   407.4   0.045       0   419.4     0.1       0
Bank Sta=   407.4,   419.4
Exp/Cntr=0.3,0.1

Type RM Length L Ch R = 1 ,2403.4,397.1,398.1,401
XS GIS Cut Line= 3
     1916380.821      205283.556     1916730.147      205075.943
     1917122.659      204907.139
#Sta/Elev= 30
       0 2753.96    39.6 2737.89    59.5 2721.81   138.8 2678.63   148.7 2669.21
   158.6 2663.02   208.1 2635.72   218.0 2634.54   228.0 2628.88   247.8 2610.83
   267.6 2599.74   297.3 2587.44   391.3 2559.25   396.4 2558.18   403.3 2558.46
   416.3 2560.57   426.2 2564.10   475.9 2572.37   495.8 2580.36   515.7 2591.76
   555.4 2604.06   585.2 2614.99   605.1 2624.81   644.8 2640.70   674.6 2654.82
   694.5 2669.38   744.2 2696.57   764.1 2705.36   774.0 2712.65   833.6 2745.73
#Mann= 3 , 0 , 0
       0     0.1       0   391.3   0.045       0   403.3     0.1       0
Bank Sta=   391.3,   403.3
Exp/Cntr=0.3,0.1

Type RM Length L Ch R = 1 ,2005.2,409.2,398.7,384.9
XS GIS Cut Line= 3
     1916578.704      205581.037     1916946.613      205388.364
     1917335.340      205257.816
#Sta/Elev= 30
       0 2700.17     9.9 2695.78    29.7 2682.02    98.9 2649.57   118.7 2635.63
   178.0 2614.29   187.9 2609.91   207.6 2596.10   217.5 2591.93   237.3 2585.19
   276.9 2575.25   296.6 2567.54   385.6 2544.70   409.3 2540.19   421.3 2538.66
   425.1 2538.31   434.8 2539.06   444.6 2542.43   473.9 2559.49   542.2 2585.14
   561.8 2595.34   620.3 2619.39   630.1 2624.34   639.9 2631.76   669.2 2644.14
   698.4 2660.54   718.0 2677.92   786.3 2719.01   796.1 2729.42   825.4 2748.59
#Mann= 3 , 0 , 0
       0     0.1       0   409.3   0.045       0   421.3     0.1       0
Bank Sta=   409.3,   421.3
Exp/Cntr=0.3,0.1

Type RM Length L Ch R = 1 ,1606.2,402.3,406.8,411.2
XS GIS Cut Line= 3
     1916887.190      205989.050     1917084.555      205829.009
     1917408.857      205351.769
#Sta/Elev= 30
       0 2658.48    19.6 2652.30    39.1 2643.23    58.6 2630.93   107.5 2609.08
   156.4 2589.89   185.7 2580.23   254.1 2561.63   313.8 2552.79   363.5 2542.81
   393.4 2534.37   410.4 2532.14   413.3 2531.95   422.4 2532.01   463.0 2549.60
   512.8 2565.90   522.7 2568.49   532.6 2569.41   552.6 2576.94   592.3 2593.36
   632.1 2614.60   642.1 2617.65   652.0 2624.54   671.9 2645.77   711.7 2677.02
   751.5 2711.82   761.5 2715.43   781.4 2731.46   811.2 2753.33   831.1 2765.05
#Mann= 3 , 0 , 0
       0     0.1       0   410.4   0.045       0   422.4     0.1       0
Bank Sta=   410.4,   422.4
Exp/Cntr=0.3,0.1

Type RM Length L Ch R = 1 ,1199.4,166.6,167,167.3
XS GIS Cut Line= 3
     1917104.906      206300.034     1917402.963      206019.228
     1917701.020      205738.421
#Sta/Elev= 30
       0 2654.96    30.0 2639.17    49.9 2632.57    69.9 2623.22    89.9 2612.06
   159.8 2586.54   179.8 2581.78   199.8 2572.37   239.7 2560.12   309.6 2540.95
   329.6 2537.79   389.5 2523.16   399.5 2520.44   419.7 2512.70   429.5 2512.46
   431.7 2512.93   449.4 2516.39   459.4 2520.85   509.4 2545.08   529.4 2558.23
   569.3 2579.03   579.3 2581.25   589.3 2584.87   609.3 2594.77   629.2 2608.69
   709.1 2654.70   729.1 2664.94   739.1 2672.04   779.0 2696.28   819.0 2722.23
#Mann= 3 , 0 , 0
       0     0.1       0   419.7   0.045       0   431.7     0.1       0
Bank Sta=   419.7,   431.7
Exp/Cntr=0.3,0.1

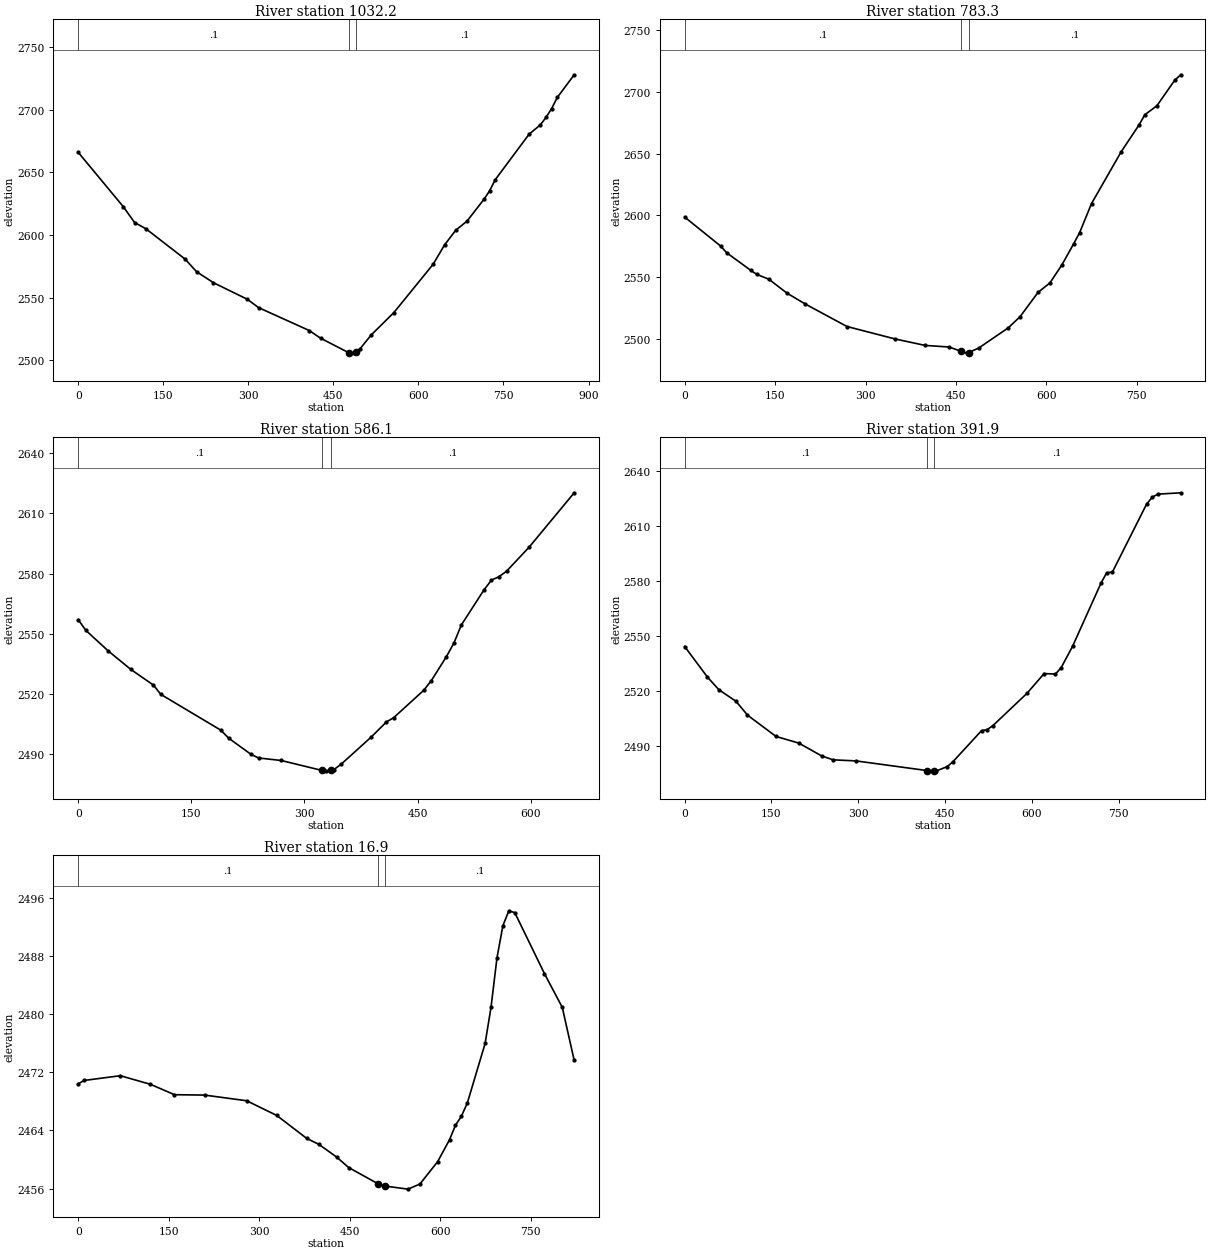
Type RM Length L Ch R = 1 ,1032.2,246.1,248.8,251.4
XS GIS Cut Line= 2
     1917176.984      206450.419     1917821.146      205858.871
#Sta/Elev= 30
       0 2665.88    79.5 2622.55    99.4 2609.94   119.3 2604.96   188.8 2580.65
   208.7 2570.70   238.5 2561.94   298.2 2548.75   318.0 2542.10   407.5 2523.82
   427.4 2517.71     478 2505.94   487.0 2505.81     490 2506.84   496.9 2509.20
   516.8 2520.36   556.5 2538.03   626.1 2576.76   646.0 2592.06   665.9 2603.84
   685.7 2611.04   715.6 2628.48   725.5 2635.17   735.4 2644.05   795.1 2680.30
   814.9 2687.74   824.9 2693.65   834.8 2700.70   844.8 2709.59   874.6 2727.66
#Mann= 3 , 0 , 0
       0     0.1       0     478   0.045       0     490     0.1       0
Bank Sta=     478,     490
Exp/Cntr=0.3,0.1

Type RM Length L Ch R = 1 ,783.3,198.5,197.3,196
XS GIS Cut Line= 3
     1917359.585      206565.133     1917674.647      206304.749
     1918012.663      206065.989
#Sta/Elev= 30
       0 2598.72    59.8 2575.19    69.8 2569.78   109.7 2555.56   119.6 2552.33
   139.6 2548.43   169.5 2537.22   199.4 2528.52   269.2 2510.14   348.9 2500.08
   398.8 2494.84   438.3 2493.57   458.9 2490.03   467.8 2488.60   470.9 2489.05
   487.6 2492.68   536.8 2509.09   556.5 2518.21   586.1 2537.78   605.8 2545.42
   625.5 2559.86   645.2 2577.11   655.1 2586.13   674.8 2609.65   724.0 2651.57
   753.6 2673.30   763.4 2681.62   783.2 2688.78   812.7 2709.41   822.6 2713.86
#Mann= 3 , 0 , 0
       0     0.1       0   458.9   0.045       0   470.9     0.1       0
Bank Sta=   458.9,   470.9
Exp/Cntr=0.3,0.1

Type RM Length L Ch R = 1 ,586.1,196.1,194.3,192.5
XS GIS Cut Line= 2
     1917572.298      206640.966     1918085.636      206230.011
#Sta/Elev= 30
       0 2557.07    10.0 2551.76    39.8 2541.48    69.7 2532.29    99.6 2524.51
   109.6 2519.82   189.3 2501.96   199.3 2498.08   229.2 2489.94   239.1 2488.16
   269.0 2486.92   323.3 2481.95   328.8 2481.61   335.3 2482.07   338.8 2482.32
   348.7 2485.07   388.6 2498.62   408.5 2506.06   418.4 2508.27   458.3 2521.93
   468.3 2526.74   488.2 2538.63   498.2 2545.44   508.1 2554.46   538.0 2571.87
   548.0 2576.78   557.9 2578.45   567.9 2581.18   597.8 2593.13   657.6 2620.24
#Mann= 3 , 0 , 0
       0     0.1       0   323.3   0.045       0   335.3     0.1       0
Bank Sta=   323.3,   335.3
Exp/Cntr=0.3,0.1

Type RM Length L Ch R = 1 ,391.9,378.5,374.8,370.5
XS GIS Cut Line= 3
     1917662.803      206848.810     1918045.820      206493.079
     1918157.809      206178.206
#Sta/Elev= 30
       0 2544.32    39.4 2527.68    59.2 2520.80    88.8 2514.52   108.5 2507.04
   157.8 2495.44   197.3 2491.81   236.7 2484.84   256.4 2482.72   295.9 2482.14
     418 2476.92     430 2476.60   434.0 2476.58   453.7 2479.04   463.6 2481.73
   512.9 2498.58   522.7 2499.16   532.6 2501.33   591.5 2518.90   621.0 2529.60
   640.7 2529.37   650.5 2532.82   670.2 2544.43   719.3 2578.79   729.2 2584.48
   739.0 2584.78   798.0 2621.69   807.8 2625.49   817.6 2627.18   856.9 2627.89
#Mann= 3 , 0 , 0
       0     0.1       0     418   0.045       0     430     0.1       0
Bank Sta=     418,     430
Exp/Cntr=0.3,0.1

Type RM Length L Ch R = 1 ,16.9,15.1,16.9,18.6
XS GIS Cut Line= 3
     1917973.825      207209.335     1918199.873      206868.667
     1918460.485      206547.984
#Sta/Elev= 30
       0 2470.41    10.0 2470.87    69.8 2471.52   119.7 2470.34   159.6 2468.91
   209.4 2468.86   279.2 2468.08   329.1 2466.06   378.9 2462.90   398.9 2462.09
   428.5 2460.34   448.2 2458.91   496.5 2456.70   508.5 2456.36   546.6 2455.94
   566.3 2456.63   595.8 2459.71   615.5 2462.72   625.3 2464.70   635.1 2465.94
   645.0 2467.76   674.5 2475.95   684.3 2480.92   694.2 2487.73   704.0 2492.13
   713.8 2494.17   723.7 2493.92   772.9 2485.54   802.4 2480.91   822.1 2473.65
#Mann= 3 , 0 , 0
       0     0.1       0   496.5   0.045       0   508.5     0.1       0
Bank Sta=   496.5,   508.5
Exp/Cntr=0.3,0.1